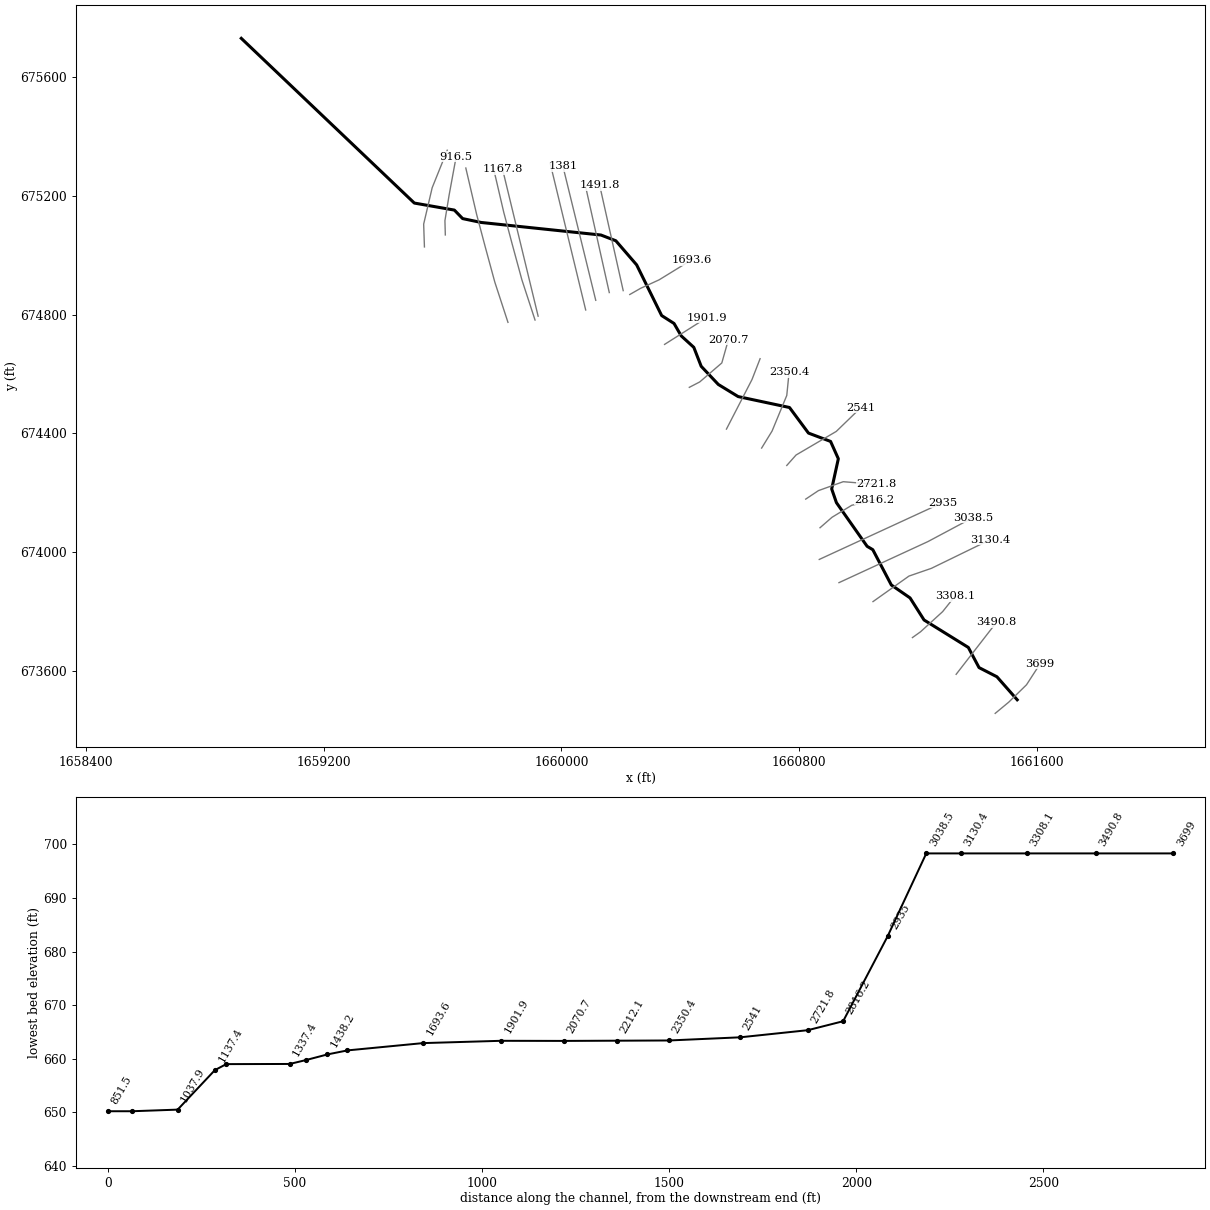
--- MHNRN.prj (project) ---

Proj Title=MHNRN
Current Plan=p01
Default Exp/Contr=0,0
English Units
Geom File=g01
Flow File=f01
Plan File=p01
BEGIN DESCRIPTION:
END DESCRIPTION:
DSS Export Rating Curves= 0
DSS Export Rating Curve Sorted= 0
DSS Export Volume Flow Curves= 0
DXF Filename=..\..\..\..\..\Engineering\Hydraulics\MHNRN\MHNRN.
DXF OffsetX= 0
DXF OffsetY= 0
DXF ScaleX= 0
DXF ScaleY= 0

--- MHNRN.p01 (plan) ---

Plan Title=Floodplain
Program Version=4.00
Geom File=g01
Flow File=f01
K Sum by GR=0
Std Step Tol=0.01
Critical Tol=0.01
Num of Std Step Trials=20
Max Error Tol=0.3
Flow Tol Ratio=0.001
Split Flow NTrial=30
Split Flow Tol=0.02
Split Flow Ratio=0.02
Log Output Level=0
Friction Slope Method=1
Unsteady Friction Slope Method=2
Unsteady Bridges Friction Slope Method=1
Global Log Level=0
CheckData=False
Run HTab=0
Run UNet=0
Run PostProcess=0
UNET Theta=0
UNET Theta Warmup=0
UNET ZTol=0
UNET ZSATol=0
UNET MxIter=0
UNET MaxInSteps=0
UNET DtIC=0
UNET DtMin=0
UNET MaxCRTS=0
UNET WFStab=0
UNET SFStab=0
UNET WFX=0
UNET SFX=0
UNET DSS MLevel=0
UNET DZMax Abort=0
UNET Convert EG Bridges=0
UNET Use Existing IB Tables=0
UNET Froude Limit=0
UNET Froude Power=0
Write IC File=0
Echo Input=False
Echo Output=False
Write Detailed=0

--- MHNRN.f01 (steady flow) ---

Flow Title=NFF Regression Equation
Program Version=4.00
Number of Profiles=1
Profile Names=P100yr
River Rch & RM=MHNRN,Main      ,3699
878.3009
River Rch & RM=MHNRN,Main      ,1693.6
910.6691
River Rch & RM=MHNRN,Main      ,1337.4
1097.146
Boundary for River Rch & Prof#=MHNRN,Main      ,1
Up Type=0
Dn Type=3
Dn Slope=0.025719

--- MHNRN.g01 (geometry) ---

Geom Title=2003 WVU SAMB 3 Meter DEM
Program Version=4.10

River Reach=MHNRN           ,Main
Reach XY= 30
     1661534.871      673503.426     1661466.603      673580.887
     1661406.336      673611.809     1661370.329      673679.614
     1661221.223      673772.096      1661174.11      673846.351
     1661110.987      673889.981     1661048.622      674008.795
     1661029.525       674020.08     1660926.203       674167.05
     1660910.253      674213.165     1660932.605      674314.923
     1660906.498      674373.191     1660832.049       674401.29
     1660768.138      674487.445     1660595.178      674524.229
     1660528.447      674565.027     1660470.829      674626.117
     1660445.981      674689.919     1660403.446      674728.656
      1660379.43      674770.272     1660337.685       674796.99
      1660253.49      674967.588     1660183.394      675048.751
     1660133.373      675068.066     1659730.046      675110.358
     1659667.546      675123.379     1659639.768      675152.025
       1659504.9      675175.704     1658922.186      675730.252

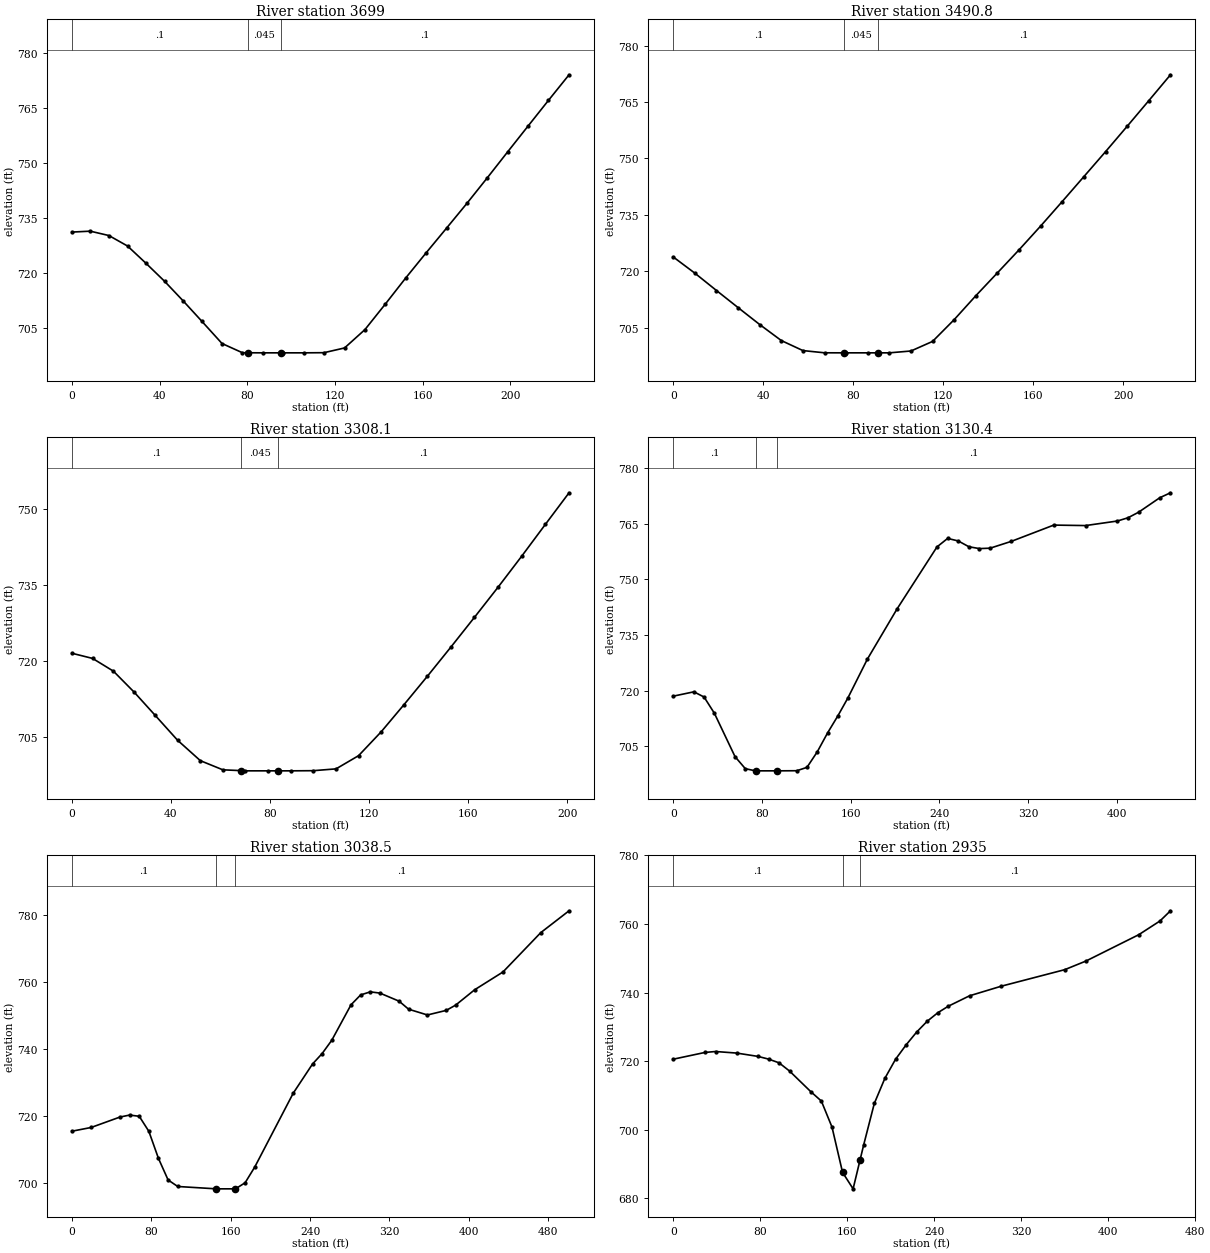
Type RM Length L Ch R = 1 ,3699    ,203.5,208.2,211.9
XS GIS Cut Line= 4
     1661460.813      673457.676     1661506.386      673495.436
     1661566.282       673554.03     1661611.854      673624.342
#Sta/Elev= 28
       0  731.17     8.4  731.42    16.9  730.23    25.4  727.38    33.8  722.69
    42.3  717.78    50.7  712.49    59.2  706.96    68.5  700.84    77.8  698.33
    80.3  698.32    87.1   698.3    95.3   698.3    96.4   698.3   105.7   698.3
     115  698.34   124.4  699.63   133.7  704.63     143  711.58   152.3  718.68
   161.6  725.52   170.9  732.23   180.2  738.98   189.5  745.94   198.8  753.01
   208.1  760.03   217.4  767.02   226.8  773.99
#Mann= 3 , 0 , 0
       0      .1       0    80.3    .045       0    95.3      .1       0
Bank Sta=80.3,95.3
XS Rating Curve= 0 ,0
Exp/Cntr=0.3,0.1

Type RM Length L Ch R = 1 ,3490.8  ,186.9,182.7,176.7
XS GIS Cut Line= 2
     1661329.302      673589.186     1661464.719      673763.665
#Sta/Elev= 26
       0   723.8     9.6  719.49    19.2  714.88    28.8  710.33    38.4  705.83
      48  701.57    57.6   698.9    67.2  698.31    75.9   698.3    76.8   698.3
    86.4   698.3    90.9   698.3      96   698.3   105.6  698.79   115.2  701.34
   124.8  707.13   134.4  713.48     144  719.57   153.6  725.69   163.2  732.02
   172.8  738.55   182.4  745.16   192.1  751.85   201.7   758.6   211.3  765.41
   220.9  772.27
#Mann= 3 , 0 , 0
       0      .1       0    75.9    .045       0    90.9      .1       0
Bank Sta=75.9,90.9
XS Rating Curve= 0 ,0
Exp/Cntr=0.3,0.1

Type RM Length L Ch R = 1 ,3308.1  ,180.3,177.7,174.7
XS GIS Cut Line= 4
     1661182.167      673712.884     1661209.511      673732.415
     1661283.729      673800.123     1661325.396      673852.207
#Sta/Elev= 25
       0  721.55     8.4  720.52    16.8     718    25.2  713.84    33.6   709.3
    42.7  704.35    51.9  700.31      61   698.5    68.4  698.34    70.1   698.3
    79.3   698.3    83.4   698.3    88.4   698.3    97.5  698.33   106.7  698.69
   115.8   701.3   124.9     706   134.1  711.36   143.6  717.01   153.1  722.78
   162.6  728.65   172.2  734.65   181.7  740.75   191.2     747   200.8  753.27
#Mann= 3 , 0 , 0
       0      .1       0    68.4    .045       0    83.4      .1       0
Bank Sta=68.4,83.4
XS Rating Curve= 0 ,0
Exp/Cntr=0.3,0.1

Type RM Length L Ch R = 1 ,3130.4  ,96.1,91.9,88.3
XS GIS Cut Line= 4
     1661049.354      673833.978     1661170.448      673919.915
     1661245.969      673945.957     1661443.886      674042.311
#Sta/Elev= 30
       0  718.48    18.6  719.65    27.8  718.24    37.1  713.85    55.7  702.14
      65  698.88    74.2   698.3    93.2   698.3   111.4  698.33   120.6  699.24
   129.9  703.44   139.2  708.55   148.5  713.17   157.4  717.93   175.1  728.49
   201.8  742.02   237.9  758.81   247.5   761.1   257.1  760.41   266.7  758.84
   276.2  758.35   285.8  758.46   304.9   760.3   343.2   764.7   371.9  764.57
   400.6   765.8   410.2  766.68   419.8  768.19   438.9   772.1   448.5  773.43
#Mann= 3 , 0 , 0
       0      .1       0    74.2    .045       0    93.2      .1       0
Bank Sta=74.2,93.2
XS Rating Curve= 0 ,0
Exp/Cntr=0.3,0.1

Type RM Length L Ch R = 1 ,3038.5  ,103.3,103.5,102.7
XS GIS Cut Line= 3
     1660934.771       673897.78     1661234.174      674035.966
     1661385.292       674116.53
#Sta/Elev= 30
       0  715.46    19.4  716.57    48.5  719.68    58.2  720.27    67.9  719.91
    77.6  715.43    87.3  707.35      97  700.94   106.7     699   145.5   698.3
   164.9   698.3   174.6  700.11   184.3  704.79   223.1   726.8   242.5  735.47
   252.2  738.59   261.9  742.54   281.3  753.11     291  756.05   300.7  756.96
   310.4   756.6   329.8  754.18   339.3   751.8   358.3  750.08   377.3  751.45
   386.8  753.03   405.9  757.59   434.4  762.88   472.5   774.6     501  781.11
#Mann= 3 , 0 , 0
       0      .1       0   145.5    .045       0   164.9      .1       0
Bank Sta=145.5,164.9
XS Rating Curve= 0 ,0
Exp/Cntr=0.3,0.1

Type RM Length L Ch R = 1 ,2935    ,116.1,118.7,121.3
XS GIS Cut Line= 2
     1660868.365      673975.905     1661283.729      674167.311
#Sta/Elev= 30
       0   720.6    29.2  722.57    38.9  722.84    58.4  722.38    77.8  721.42
    87.6  720.63    97.3  719.54     107  717.13   126.5  711.13   136.2   708.4
     146   700.8   155.7   687.6   165.4  682.81   171.8  691.24   175.2  695.72
   184.9   707.7   194.6  715.01   204.4  720.56   214.1  724.75   223.8  728.49
   233.5  731.65   243.3  734.14     253  736.05   272.5  739.08   301.6  741.87
     360  746.69   379.5   749.2   428.2   756.9   447.6  760.88   457.3  763.86
#Mann= 3 , 0 , 0
       0      .1       0   155.7    .045       0   171.8      .1       0
Bank Sta=155.7,171.8
XS Rating Curve= 0 ,0
Exp/Cntr=0.3,0.1

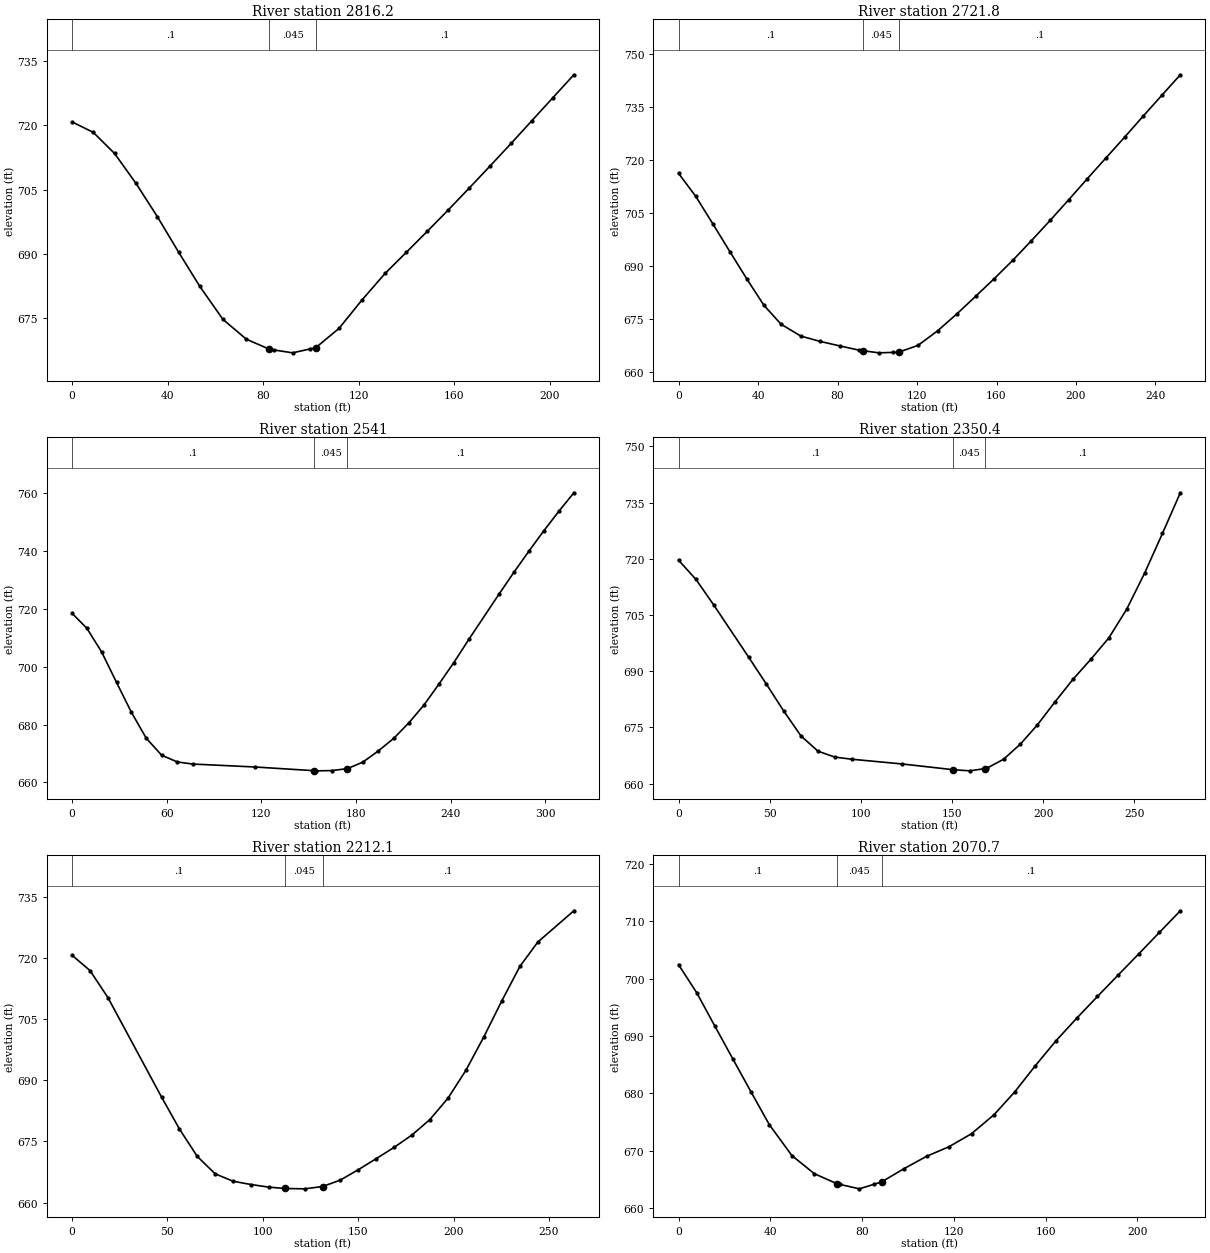
Type RM Length L Ch R = 1 ,2816.2  ,98.5,94.4,91.5
XS GIS Cut Line= 4
     1660870.969      674082.676     1660911.334      674117.832
      1660977.74      674158.196     1661054.563      674176.426
#Sta/Elev= 26
       0  720.78     8.9  718.34    17.8  713.43    26.8  706.44    35.7  698.74
    44.6  690.47    53.5  682.48    63.2  674.78      73  670.17    82.7  667.82
    84.7  667.65    92.4  666.99    99.7   667.9   102.1   668.2   111.8  672.67
   121.5  679.34   131.2  685.53     140  690.39   148.8   695.3   157.6  700.28
   166.3  705.33   175.1  710.51   183.9  715.76   192.6  721.06   201.4  726.41
   210.2  731.76
#Mann= 3 , 0 , 0
       0      .1       0    82.7    .045       0   102.1      .1       0
Bank Sta=82.7,102.1
XS Rating Curve= 0 ,0
Exp/Cntr=0.3,0.1

Type RM Length L Ch R = 1 ,2721.8  ,180.3,180.8,181.1
XS GIS Cut Line= 4
     1660822.792       674179.03     1660865.761      674207.676
     1660949.094      674237.623     1661061.073      674228.509
#Sta/Elev= 30
       0  716.14     8.6  709.67    17.2   701.9    25.8     694    34.4  686.21
      43  678.76    51.6  673.42    61.5  670.07    71.3  668.55    81.2  667.27
      91  666.06    92.7  665.93   100.8  665.32   107.7  665.44   110.7  665.49
   120.5  667.43   130.4  671.57   140.2  676.41   149.6  681.38   158.9  686.34
   168.3  691.58   177.6  697.09     187  702.82   196.4   708.7   205.7  714.62
   215.1  720.51   224.5   726.4   233.8  732.33   243.2  738.24   252.5  744.04
#Mann= 3 , 0 , 0
       0      .1       0    92.7    .045       0   110.7      .1       0
Bank Sta=92.7,110.7
XS Rating Curve= 0 ,0
Exp/Cntr=0.3,0.1

Type RM Length L Ch R = 1 ,2541    ,171.3,190.6,206.1
XS GIS Cut Line= 4
      1660758.99      674292.311      1660790.24      674327.467
     1660925.657      674406.894     1661007.688      674486.321
#Sta/Elev= 28
       0  718.45     9.4  713.29    18.8  705.04    28.2  694.56    37.6  684.25
      47   675.3    56.8  669.39    66.7  667.07    76.5  666.34   115.7  665.33
   153.2  664.05     155  663.99   164.8  664.08   174.6  664.76   184.4     667
   194.2  670.87     204  675.23   213.5  680.55   223.1  686.71   232.6  693.96
   242.1  701.44   251.6  709.44   270.6  724.98   280.2  732.66   289.7  739.96
   299.2  747.04   308.7  753.76   318.2  760.14
#Mann= 3 , 0 , 0
       0      .1       0   153.2    .045       0   174.6      .1       0
Bank Sta=153.2,174.6
XS Rating Curve= 0 ,0
Exp/Cntr=0.3,0.1

Type RM Length L Ch R = 1 ,2350.4  ,139.8,138.3,135.9
XS GIS Cut Line= 4
     1660674.354      674350.905     1660709.511      674408.196
      1660758.99      674527.988     1660766.802      674606.113
#Sta/Elev= 26
       0  719.62     9.6  714.46    19.2  707.74    38.4  693.78      48  686.69
    57.6  679.44    67.2   672.7    76.5  668.65    85.7  667.07      95   666.5
   122.8  665.23   150.5  663.71   159.8   663.4   168.1     664     169  664.07
   178.3  666.48   187.6  670.56   196.8  675.61   206.6  681.84   216.4  687.82
   226.3  693.22   236.1  698.89   245.9  706.55   255.7  716.15   265.5  726.76
   275.3   737.6
#Mann= 3 , 0 , 0
       0      .1       0   150.5    .045       0   168.1      .1       0
Bank Sta=150.5,168.1
XS Rating Curve= 0 ,0
Exp/Cntr=0.3,0.1

Type RM Length L Ch R = 1 ,2212.1  ,149.8,141.4,132.4
XS GIS Cut Line= 3
     1660555.865      674414.707     1660641.802      674581.373
     1660669.146      674651.686
#Sta/Elev= 26
       0  720.79     9.4  717.03    18.8  710.38    46.9  685.92    56.3  678.06
    65.6  671.34      75  667.05    84.4  665.23    93.8  664.42   103.1  663.78
   111.4  663.45   121.9  663.36   131.3  663.93   140.6  665.51     150  668.06
   159.4  670.78   168.8  673.56   178.1  676.58   187.5  680.38     197  685.63
   206.4  692.49   215.8  700.71   225.2  709.54   234.7  718.04   244.1  724.04
     263  731.73
#Mann= 3 , 0 , 0
       0      .1       0   111.4    .045       0   131.3      .1       0
Bank Sta=111.4,131.3
XS Rating Curve= 0 ,0
Exp/Cntr=0.3,0.1

Type RM Length L Ch R = 1 ,2070.7  ,171.6,168.8,164.9
XS GIS Cut Line= 4
     1660430.865      674555.332     1660466.021      674573.561
      1660540.24      674637.363     1660562.375      674715.488
#Sta/Elev= 27
       0  702.42     7.9  697.55    15.8  691.73    23.8  685.89    31.7  680.15
    39.6   674.5    49.4  669.13    59.2  665.96      69  664.22    70.4  664.09
    78.8  663.32    85.4  664.14    88.5  664.53    98.3  666.85   108.1  668.99
   117.9  670.67   127.7  672.94   137.5  676.25   146.5  680.22   155.5   684.8
   164.5  689.15   173.6  693.11   182.6  696.89   191.6  700.61   200.6  704.32
   209.6  708.06   218.7  711.83
#Mann= 3 , 0 , 0
       0      .1       0      69    .045       0    88.5      .1       0
Bank Sta=69,88.5
XS Rating Curve= 0 ,0
Exp/Cntr=0.3,0.1

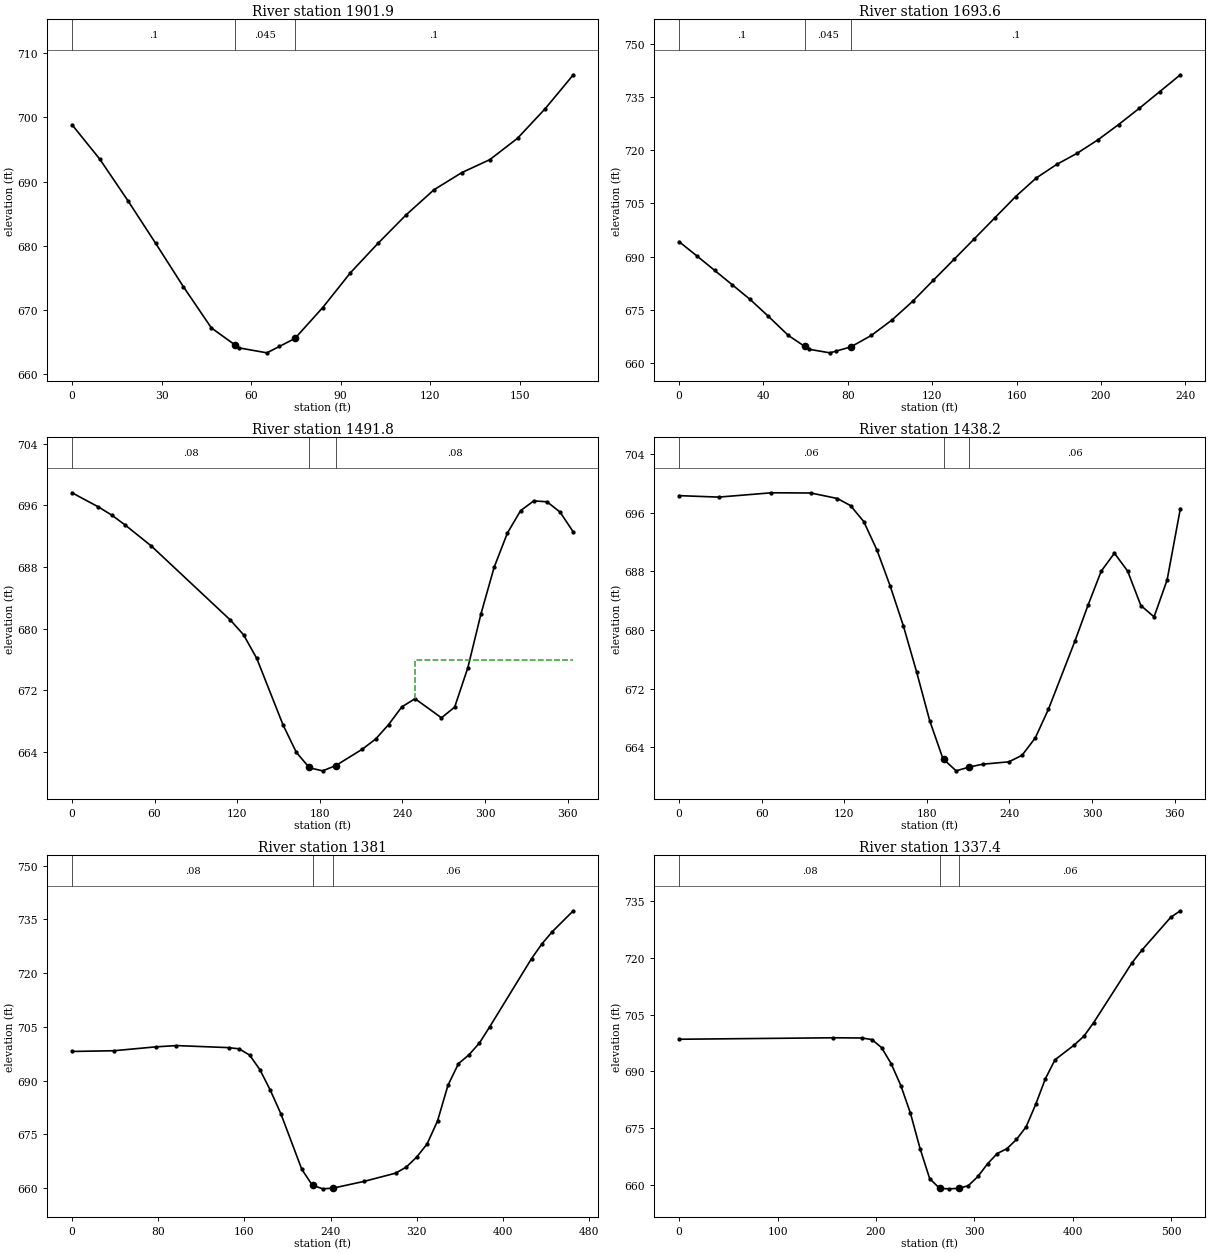
Type RM Length L Ch R = 1 ,1901.9  ,211.1,208.3,204.6
XS GIS Cut Line= 2
     1660347.532      674699.863     1660489.459      674789.707
#Sta/Elev= 21
       0  698.86     9.3   693.5    18.7  687.05      28  680.41    37.3  673.65
    46.7  667.22    54.5  664.61      56  664.11    65.3  663.34    69.5  664.34
    74.7  665.58      84  670.38    93.3  675.81   102.6  680.42     112  684.84
   121.3  688.73   130.6   691.4     140  693.42   149.3  696.75   158.6  701.37
     168  706.64
#Mann= 3 , 0 , 0
       0      .1       0    54.5    .045       0    74.7      .1       0
Bank Sta=54.5,74.7
XS Rating Curve= 0 ,0
Exp/Cntr=0.3,0.1

Type RM Length L Ch R = 1 ,1693.6  ,165,201.8,234
XS GIS Cut Line= 4
     1660230.344      674867.832     1660266.802      674888.665
     1660329.302      674917.311     1660437.375      674983.717
#Sta/Elev= 28
       0  694.21     8.4  690.22    16.8  686.15    25.2  682.08    33.6  677.98
      42  673.38    51.8   667.8    59.6   664.7    61.6  663.91    71.5  662.91
    74.6  663.43    81.3  664.55    91.1   667.8   100.9  672.15   110.7  677.41
   120.5  683.34   130.3  689.21     140  695.06   149.8     701   159.5   706.9
   169.3  712.15     179  715.97   188.8  719.15   198.6  722.92   208.3  727.18
   218.1  731.75   227.8  736.45   237.6  741.21
#Mann= 3 , 0 , 0
       0      .1       0    59.6    .045       0    81.3      .1       0
Bank Sta=59.6,81.3
XS Rating Curve= 0 ,0
Exp/Cntr=0.3,0.1

Type RM Length L Ch R = 1 ,1491.8  ,58.6,53.6,51.6
XS GIS Cut Line= 2
     1660208.209      674880.853     1660128.782      675236.321
#Sta/Elev= 30
       0  697.63    19.2  695.79    28.8  694.74    38.3  693.49    57.5  690.74
     115  681.12   124.6  679.21   134.2  676.14   153.4  667.47     163  663.94
     172  662.05   172.5  661.94   182.1  661.55   191.7  662.24   210.9  664.36
   220.5  665.66     230  667.55   239.6  669.85   249.2  670.91   268.4  668.43
     278  669.82   287.6  674.95   297.1  681.91   306.7  687.97   316.3   692.4
   325.9  695.31   335.5  696.58   345.1  696.46   354.6  695.12   364.2  692.54
#Mann= 3 , 0 , 0
       0     .08       0     172    .045       0   191.7     .08       0
#XS Ineff= 2 , 0
                          249.07          675.92
Permanent Ineff=
       F       F
Bank Sta=172,191.7
XS Rating Curve= 0 ,0
Exp/Cntr=0.3,0.1

Type RM Length L Ch R = 1 ,1438.2  ,57.3,57.2,58.3
XS GIS Cut Line= 2
     1660161.334      674874.342     1660081.907      675229.811
#Sta/Elev= 30
       0   698.3    28.8   698.1    67.1  698.69    95.8  698.66     115  697.91
   124.6  696.94   134.2  694.76   143.8  690.87   153.4  685.97     163  680.53
   172.5  674.33   182.1  667.63   191.7  662.46   192.2  662.37   201.3   660.8
   210.9  661.32   220.5   661.7   239.6  662.03   249.2  662.92   258.8  665.29
   268.4  669.21   287.6  678.48   297.1  683.36   306.7  688.01   316.3  690.46
   325.9  688.02   335.5  683.33   345.1  681.78   354.6  686.82   364.2  696.53
#Mann= 3 , 0 , 0
       0     .06       0   192.2    .045       0   210.9     .06       0
Bank Sta=192.2,210.9
XS Rating Curve= 0 ,0
Exp/Cntr=0.3,0.1

Type RM Length L Ch R = 1 ,1381    ,42.4,43.6,42.3
XS GIS Cut Line= 2
     1660115.761      674848.301     1660005.084      675300.123
#Sta/Elev= 30
       0  698.11    38.8  698.31    77.5  699.39    96.9  699.75   145.4  699.18
   155.1  698.83   164.8   697.1   174.4  692.99   184.1  687.22   193.8  680.71
   213.2  665.22   222.9   660.8   223.9  660.69   232.6  659.75   242.3  659.95
   271.4  661.86   300.4  664.14   310.1  665.81   319.8   668.6   329.5  672.28
   339.2  678.72   348.9  688.68   358.6  694.69   368.3  697.16     378  700.44
   387.6  704.98   426.4  724.02   436.1  728.16   445.8  731.59   465.2  737.39
#Mann= 3 , 0 , 0
       0     .08       0   223.9    .045       0   242.3     .06       0
Bank Sta=223.9,242.3
XS Rating Curve= 0 ,0
Exp/Cntr=0.3,0.1

Type RM Length L Ch R = 1 ,1337.4  ,169.6,169.6,169.6
XS GIS Cut Line= 2
     1660081.907      674815.748     1659962.115       675310.54
#Sta/Elev= 30
       0  698.49   156.6  698.88     186  698.82   195.8   698.4   205.6  696.31
   215.4  692.04   225.2  686.28     235  678.95   244.8   669.6   254.5  661.72
   264.7  659.12   274.1  659.02   283.9  659.14   293.7  659.85   303.5  662.28
   313.3  665.63   323.1  668.34   332.9   669.6   342.6  672.04   352.4  675.36
   362.2  681.31     372  688.06   381.8  693.08   401.4  696.98   411.2  699.31
     421  702.86   460.1   718.7   469.9  721.96   499.3  730.66   509.1  732.39
#Mann= 3 , 0 , 0
       0     .08       0   264.7    .045       0   283.9     .06       0
Bank Sta=264.7,283.9
XS Rating Curve= 0 ,0
Exp/Cntr=0.3,0.1

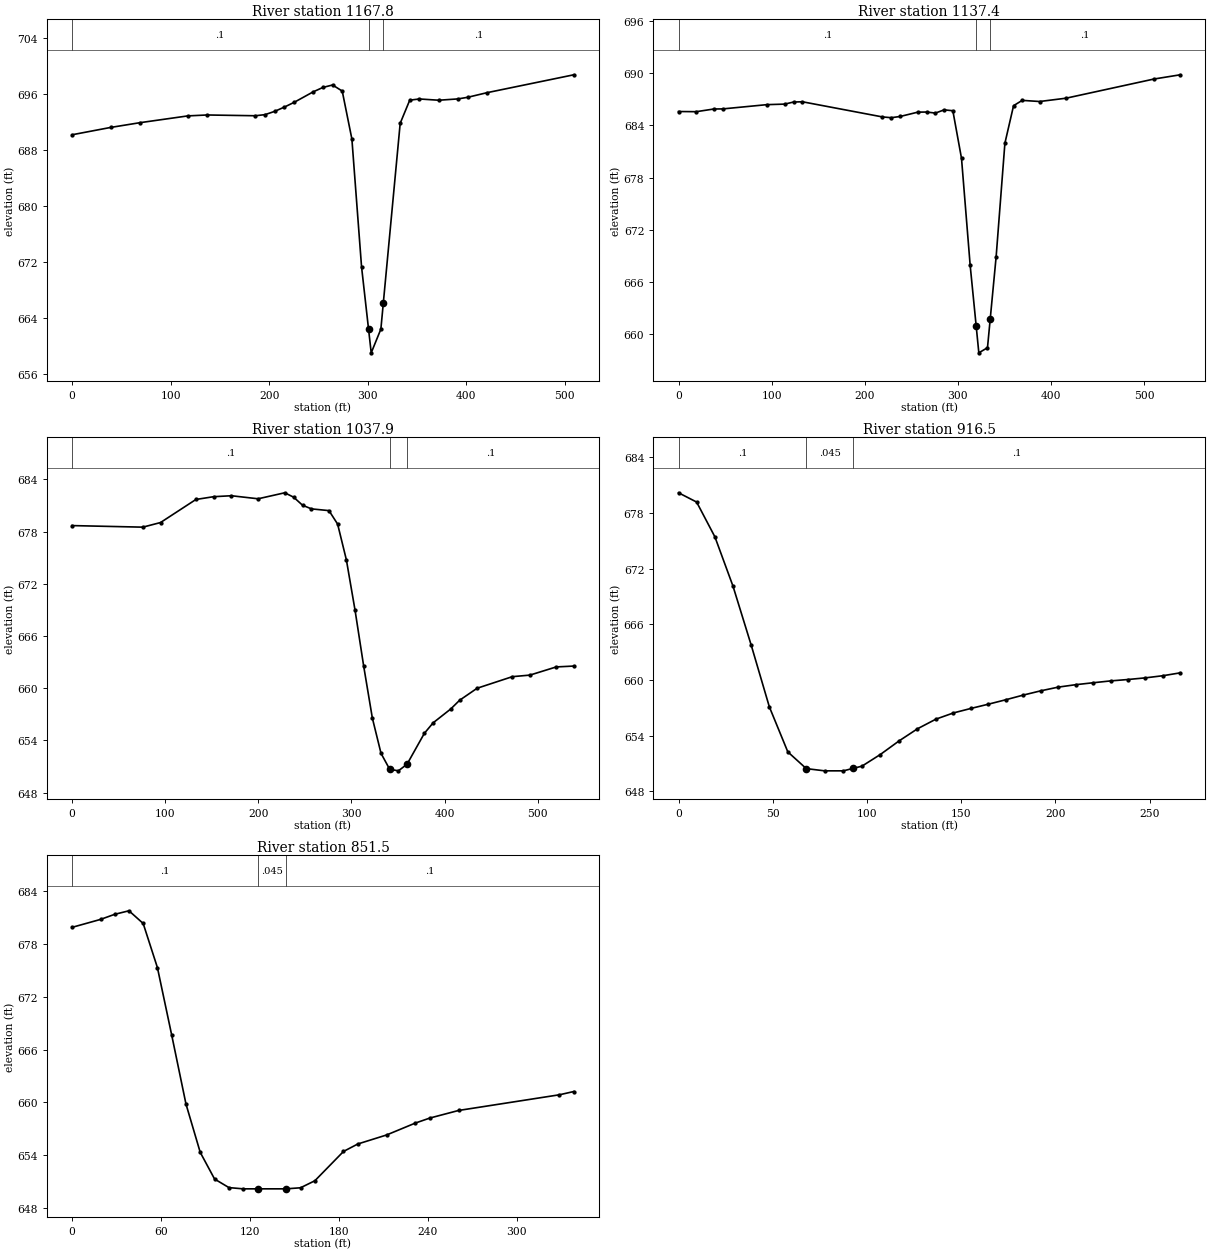
Type RM Length L Ch R = 1 ,1167.8  ,29.8,30.4,31.3
XS GIS Cut Line= 2
      1659921.75      674794.915     1659801.959      675289.707
#Sta/Elev= 28
       0  690.18    39.2  691.23    68.5   691.9   117.5  692.88   137.1  693.01
     186   692.9   195.8  693.06   205.6  693.53   215.4  694.14   225.2  694.81
   244.8  696.33   254.5  696.95   264.3   697.3   274.1  696.43   283.9  689.57
   293.7  671.29   300.8  662.38   303.5  658.99   313.3  662.38   315.8  666.15
   332.9  691.82   342.6  695.13   352.4   695.3     372  695.12   391.6  695.31
   401.4  695.54     421   696.2   509.1  698.76
#Mann= 3 , 0 , 0
       0      .1       0   300.8    .045       0   315.8      .1       0
Bank Sta=300.8,315.8
XS Rating Curve= 0 ,0
Exp/Cntr=0.3,0.1

Type RM Length L Ch R = 1 ,1137.4  ,98.8,99.5,99.5
XS GIS Cut Line= 5
     1659911.334      674781.894     1659867.063      674917.311
     1659834.511      675037.103     1659805.865      675145.176
     1659769.407      675301.426
#Sta/Elev= 30
       0  685.59      19  685.57      38  685.88    47.5  685.89      95  686.38
     114  686.44   123.5  686.68     133  686.71   218.9  684.97   228.4  684.88
     238  685.02   257.1  685.52   266.6  685.53   275.9  685.41   285.2  685.78
   294.6  685.68   303.9  680.21   313.2  667.92   319.7   660.9   322.5  657.87
   331.8  658.46   334.7  661.72   341.1  668.92   350.5  681.95   359.8  686.26
   369.1  686.87   387.8  686.74   416.2  687.12   510.5  689.32   538.9  689.81
#Mann= 3 , 0 , 0
       0      .1       0   319.7    .045       0   334.7      .1       0
Bank Sta=319.7,334.7
XS Rating Curve= 0 ,0
Exp/Cntr=0.3,0.1

Type RM Length L Ch R = 1 ,1037.9  ,132.4,121.4,110.4
XS GIS Cut Line= 5
     1659820.188      674774.082     1659775.917      674909.498
     1659743.365       675029.29     1659714.719      675137.363
     1659678.261      675293.613
#Sta/Elev= 30
       0  678.68      76   678.5      95  679.03     133  681.68     152     682
   171.1  682.11   199.8  681.76   228.4  682.45     238  681.94   247.5  681.02
   257.1   680.6   275.9   680.4   285.2  678.85   294.6  674.74   303.9  668.96
   313.2  662.52   322.5  656.56   331.8  652.51   341.1  650.68   350.5   650.5
   359.8  651.27   378.4  654.82   387.8  656.02   406.7  657.61   416.2  658.61
     435  659.99   472.8  661.32   491.7   661.5     520  662.44   538.9  662.54
#Mann= 3 , 0 , 0
       0      .1       0   341.1    .045       0   359.8      .1       0
Bank Sta=341.1,359.8
XS Rating Curve= 0 ,0
Exp/Cntr=0.3,0.1

Type RM Length L Ch R = 1 ,916.5   ,66.5,65,63.4
XS GIS Cut Line= 4
      1659609.25      675068.353     1659607.948       675116.53
     1659622.271      675203.769     1659645.709      675331.373
#Sta/Elev= 30
       0  680.16     9.6  679.16    19.3  675.41    28.9   670.1    38.6  663.72
    48.2  657.09      58  652.24    67.8  650.44    77.5   650.2    87.5   650.2
    92.5  650.46    97.3   650.7   107.1  651.96     117  653.42   126.8  654.73
   136.6  655.77   145.9  656.44   155.1  656.92   164.4  657.38   173.7  657.86
   182.9  658.36   192.2  658.82   201.5  659.22   210.7  659.48     220  659.69
   229.3  659.89   238.5  660.04   247.8  660.22   257.1  660.45   266.3  660.76
#Mann= 3 , 0 , 0
       0      .1       0    67.8    .045       0    92.5      .1       0
Bank Sta=67.8,92.5
XS Rating Curve= 0 ,0
Exp/Cntr=0.3,0.1

Type RM Length L Ch R = 1 ,851.5   ,863.5,851.5,839.2
XS GIS Cut Line= 4
     1659538.938      675027.988     1659536.334      675104.811
     1659564.979      675227.207     1659615.761      675353.509
#Sta/Elev= 24
       0  679.86    19.2  680.76    28.8  681.34    38.4  681.74      48   680.3
    57.6   675.3    67.3   667.6    76.9  659.81    86.5  654.34    96.2  651.31
   105.9  650.34   115.5   650.2   125.2   650.2   144.4   650.2   154.2  650.32
   163.9  651.12   183.2  654.44   192.9  655.29   212.3  656.31   231.7  657.66
   241.5  658.23   260.9  659.09     329  660.87   338.7  661.24
#Mann= 3 , 0 , 0
       0      .1       0   125.2    .045       0   144.4      .1       0
Bank Sta=125.2,144.4
XS Rating Curve= 0 ,0
Exp/Cntr=0.3,0.1

Chan Stop Cuts=-1
Use User Specified Reach Order=0
Composite Channel Slope=5